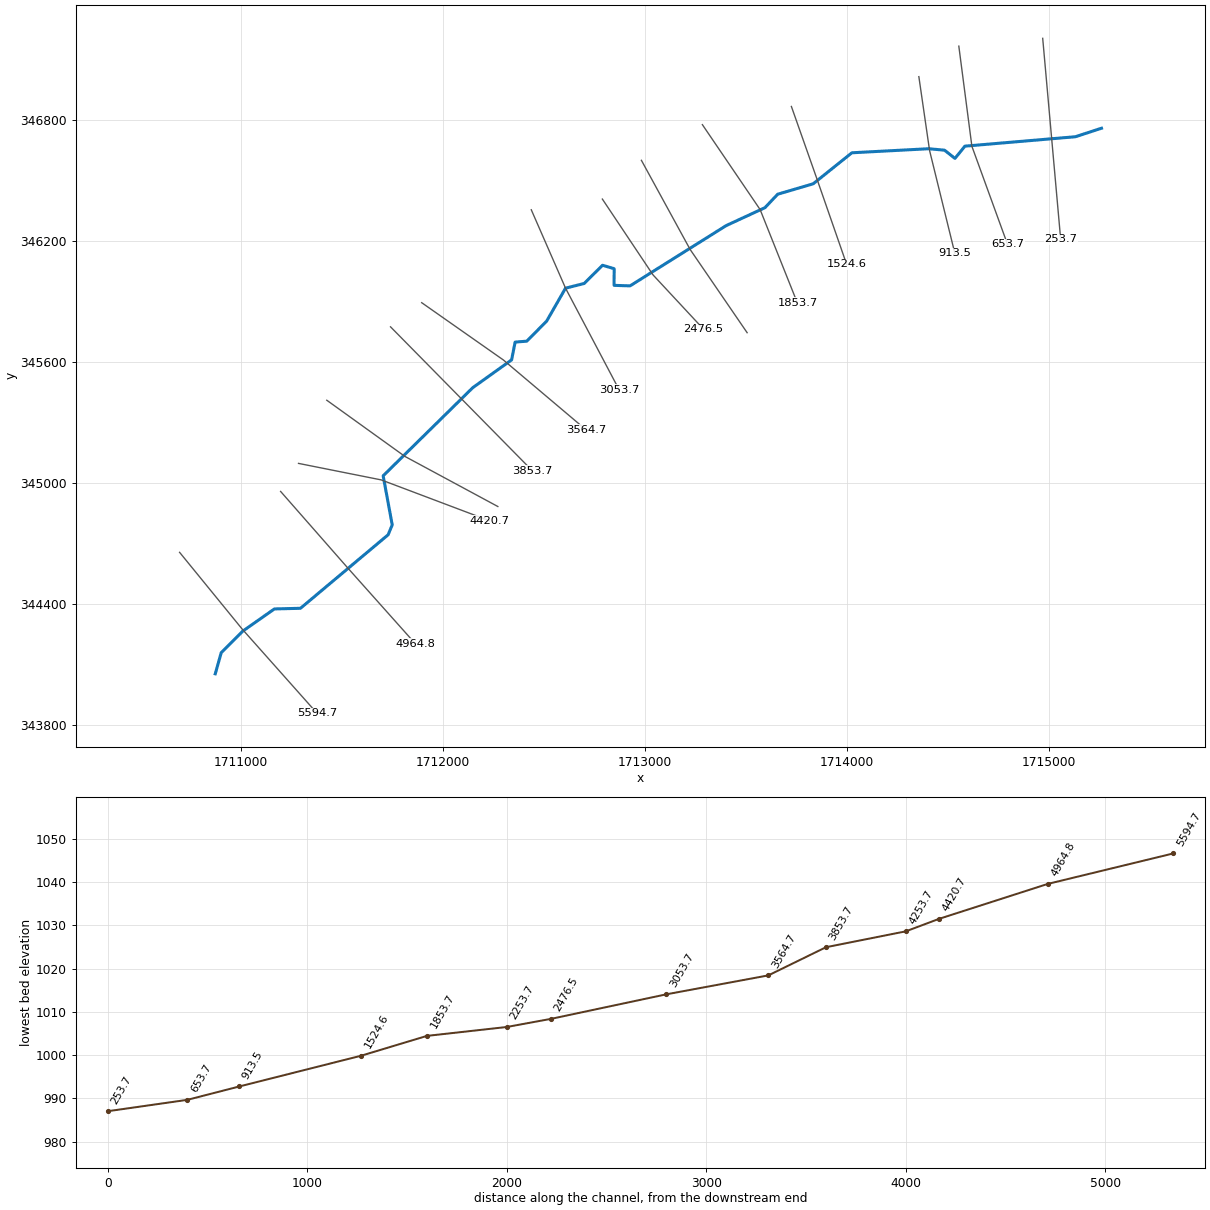
--- BgIndanCr.prj (project) ---

Proj Title=BgIndanCr
Current Plan=p01
Geom File=g01
Flow File=f01
Plan File=p01
DSS Export Rating Curves=0
DSS Export Rating Curve Sorted=0
DSS Export Volume Flow Curves=0
DXF OffsetX=0
DXF OffsetY=0
DXF ScaleX=0
DXF ScaleY=0

--- BgIndanCr.p01 (plan) ---

Plan Title=Floodplain
Program Version=4.00
Geom File=g01
Flow File=f01
K Sum by GR=0
Std Step Tol=0.01
Critical Tol=0.01
Num of Std Step Trials=20
Max Error Tol=0.3
Flow Tol Ratio=0.001
Split Flow NTrial=30
Split Flow Tol=0.02
Split Flow Ratio=0.02
Log Output Level=0
Friction Slope Method=1
Unsteady Friction Slope Method=2
Unsteady Bridges Friction Slope Method=1
Global Log Level=0
CheckData=False
Run HTab=0
Run UNet=0
Run PostProcess=0
UNET Theta=0
UNET Theta Warmup=0
UNET ZTol=0
UNET ZSATol=0
UNET MxIter=0
UNET MaxInSteps=0
UNET DtIC=0
UNET DtMin=0
UNET MaxCRTS=0
UNET WFStab=0
UNET SFStab=0
UNET WFX=0
UNET SFX=0
UNET DSS MLevel=0
UNET DZMax Abort=0
UNET Convert EG Bridges=0
UNET Use Existing IB Tables=0
UNET Froude Limit=0
UNET Froude Power=0
Write IC File=0
Echo Input=False
Echo Output=False
Write Detailed=0

--- BgIndanCr.f01 (steady flow) ---

Flow Title=NFF Regression Equation
Program Version=4.00
Number of Profiles=1
Profile Names=P100yr
River Rch & RM=BgIndanCr,Main      ,5594.7
839.8998
River Rch & RM=BgIndanCr,Main      ,4420.7
889.1939
River Rch & RM=BgIndanCr,Main      ,3053.7
986.0567
River Rch & RM=BgIndanCr,Main      ,253.7
1040.488
Boundary for River Rch & Prof#=BgIndanCr,Main      ,1
Up Type=0
Dn Type=3
Dn Slope=0.010105

--- BgIndanCr.g01 (geometry) ---

Geom Title=USGS 3m DEM
Program Version=4.00

River Reach=BgIndanCr     ,Main
Reach XY= 30
     1710873.464      344055.487     1710902.966      344160.369
     1711009.354      344266.977     1711166.079      344377.320
     1711295.219      344380.501     1711728.860      344744.931
     1711749.333      344793.917     1711704.441      345037.605
     1712147.894      345474.673     1712340.139      345612.523
     1712357.644      345700.702     1712415.313      345705.289
     1712513.852      345805.195     1712607.115      345968.179
     1712699.159      345991.395     1712790.161      346081.764
     1712847.770      346064.784     1712847.220      345982.211
     1712926.319      345979.565     1713402.336      346278.593
     1713593.969      346367.344     1713657.146      346434.205
     1713832.690      346485.822     1714024.401      346639.686
     1714405.450      346659.771     1714482.992      346652.438
     1714534.345      346611.669     1714583.683      346672.522
     1715130.780      346719.258     1715259.578      346761.447

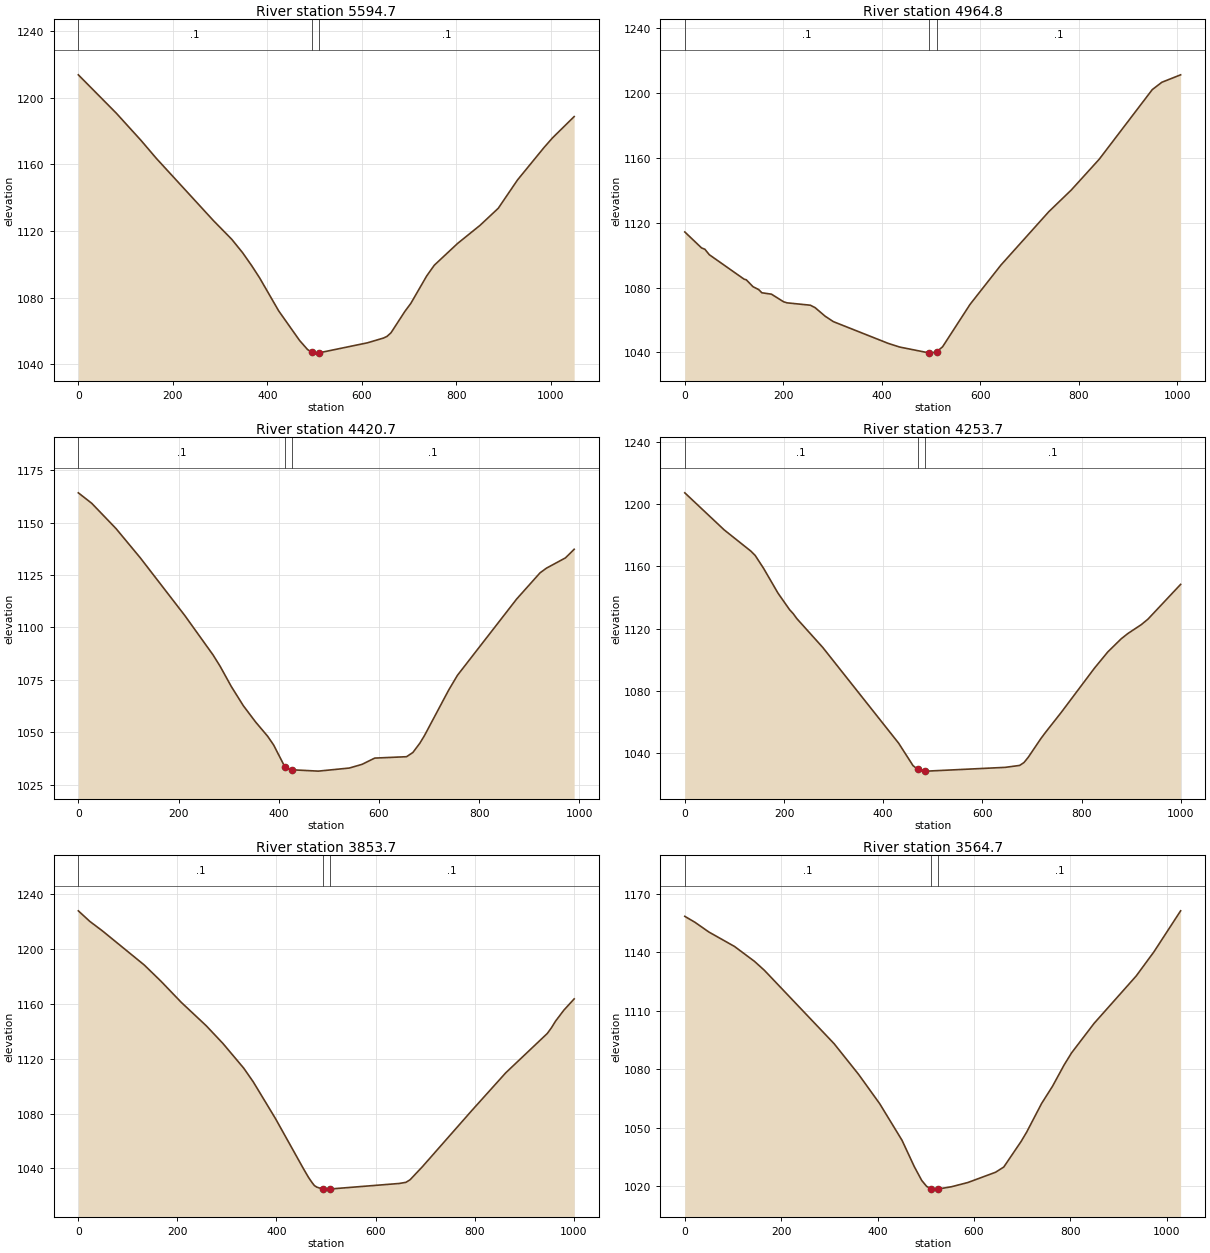
Type RM Length L Ch R = 1 ,5594.7,629.361,629.888,630.053
XS GIS Cut Line= 3
     1710696.996      344657.989     1711006.344      344277.904
     1711377.848      343859.343
#Sta/Elev= 30
       0 1213.70    80.1 1190.76   133.3 1174.15   165.2 1163.53   286.3 1126.11
   324.8 1114.98   347.6    1107   367.0 1099.16   383.9 1091.77   424.1 1072.04
   468.3 1054.29   485.3 1048.80   494.3 1047.29   503.1 1046.67   509.3 1046.83
   612.2 1052.87   646.2 1055.74   653.4 1056.71   661.8 1058.85   691.5 1071.81
   703.9 1076.54   737.5 1093.02   753.5 1099.42   802.7 1112.46   850.3 1123.35
   888.9 1133.59   929.7 1150.61   986.0 1170.13  1003.9 1175.89  1049.6 1188.63
#Mann= 3 , 0 , 0
       0     0.1       0   494.3   0.045       0   509.3     0.1       0
Bank Sta=   494.3,   509.3
Exp/Cntr=0.3,0.1

Type RM Length L Ch R = 1 ,4964.8,529.391,544.071,554.725
XS GIS Cut Line= 3
     1711196.892      344960.147     1711531.111      344578.448
     1711863.139      344205.553
#Sta/Elev= 30
       0 1114.36    34.0 1104.51    40.7 1103.70    49.8 1100.32   120.4 1085.23
   124.8 1084.86   138.4 1080.61   150.1 1078.78   156.4 1076.85   176.0 1075.97
   200.5 1071.30   207.6 1070.63   254.9 1069.17   264.6 1067.66   284.7 1062.44
   301.5 1059.05   412.8 1045.64   436.1 1043.37   496.7 1039.69   498.9 1039.61
   511.7 1040.54   523.3 1043.50   579.1 1069.68   641.8 1093.94   738.9 1126.83
   784.6 1140.23   841.3 1159.20   949.1 1202.19   968.5 1206.70  1006.6 1211.29
#Mann= 3 , 0 , 0
       0     0.1       0   496.7   0.045       0   511.7     0.1       0
Bank Sta=   496.7,   511.7
Exp/Cntr=0.3,0.1

Type RM Length L Ch R = 1 ,4420.7,176.453,167.075,164.69
XS GIS Cut Line= 3
     1711285.629      345099.123     1711695.296      345017.190
     1712230.273      344814.766
#Sta/Elev= 30
       0 1164.15    26.7 1159.17    75.1 1147.15   123.6 1133.20   212.6 1105.67
   268.9 1086.92   283.2 1081.45   305.2 1071.93   329.4 1062.71   353.6 1055.03
   377.8 1048.20   389.9 1043.99   412.2 1033.60   415.3 1032.62   427.2 1032.17
   479.1 1031.54   540.9 1033.01   566.3 1034.76   591.7 1037.75   655.2 1038.41
   667.9 1040.43   681.7 1044.83   690.9 1048.44   739.2 1070.11   756.7 1077.16
   875.1 1113.57   921.7 1126.02   934.4 1128.24   972.5 1133.16   989.8 1137.25
#Mann= 3 , 0 , 0
       0     0.1       0   412.2   0.045       0   427.2     0.1       0
Bank Sta=   412.2,   427.2
Exp/Cntr=0.3,0.1

Type RM Length L Ch R = 1 ,4253.7,403.875,400,392.994
XS GIS Cut Line= 3
     1711425.398      345412.398     1711812.163      345133.717
     1712272.027      344885.314
#Sta/Elev= 30
       0 1207.17    79.5 1183.37   133.4 1169.71   141.9 1166.99   158.9 1158.69
   187.8 1142.84   211.2 1132.21   218.4 1129.70   225.9 1126.45   278.0 1108.02
   431.1 1046.53   460.0 1032.19   469.2 1029.85   474.6 1028.81   484.2 1028.72
   488.3 1028.64   645.9 1031.06   675.0 1032.30   683.8 1034.19   692.5 1037.63
   717.7 1049.51   727.6 1053.72   758.2 1066.07   825.6 1094.65   852.6 1105.10
   879.6 1113.52   893.1 1116.92   920.1 1122.61   933.6 1126.15   999.4 1148.44
#Mann= 3 , 0 , 0
       0     0.1       0   469.2   0.045       0   484.2     0.1       0
Bank Sta=   469.2,   484.2
Exp/Cntr=0.3,0.1

Type RM Length L Ch R = 1 ,3853.7,286.763,288.949,291.122
XS GIS Cut Line= 3
     1711740.926      345776.422     1712091.861      345419.569
     1712442.797      345062.715
#Sta/Elev= 30
       0 1227.71    23.2    1220    48.4 1213.17   133.1 1188.25   166.9 1176.41
   207.9 1161.00   258.3 1143.96   291.9 1131.10   333.9 1113.10   353.2 1103.09
   398.1 1076.31   454.8 1039.65   464.7 1033.54   471.7 1029.83   476.6 1027.55
   481.4 1026.44     493 1025.05   498.0 1024.97     508 1025.05   647.9 1029.09
   661.3 1029.92   669.7 1031.77   694.9 1041.41   793.4 1081.83   862.8 1109.67
   946.7 1138.34   955.1 1142.49   963.5 1147.38   980.3 1155.38  1001.0 1163.54
#Mann= 3 , 0 , 0
       0     0.1       0     493   0.045       0     508     0.1       0
Bank Sta=     493,     508
Exp/Cntr=0.3,0.1

Type RM Length L Ch R = 1 ,3564.7,521.739,511.051,500.949
XS GIS Cut Line= 3
     1711895.116      345896.240     1712299.748      345611.825
     1712707.312      345266.807
#Sta/Elev= 30
       0 1158.55    20.6 1155.57    50.0 1150.49   103.2 1143.07   144.5 1135.44
   165.2 1130.81   309.7 1093.16   360.9 1077.27   404.5 1062.26   450.6 1043.55
   476.1 1030.00   491.5 1022.91   501.6 1019.89   510.3 1018.68   522.4 1018.45
   525.3 1018.48   553.5 1019.69   587.3 1021.85   644.8 1027.13   661.7 1029.80
   697.5 1042.87   709.1 1047.68   740.2 1062.44   762.8 1071.26   786.9 1082.22
   802.4 1088.44   849.1 1103.58   936.4 1127.91   973.2 1140.31  1028.6 1161.38
#Mann= 3 , 0 , 0
       0     0.1       0   510.3   0.045       0   525.3     0.1       0
Bank Sta=   510.3,   525.3
Exp/Cntr=0.3,0.1

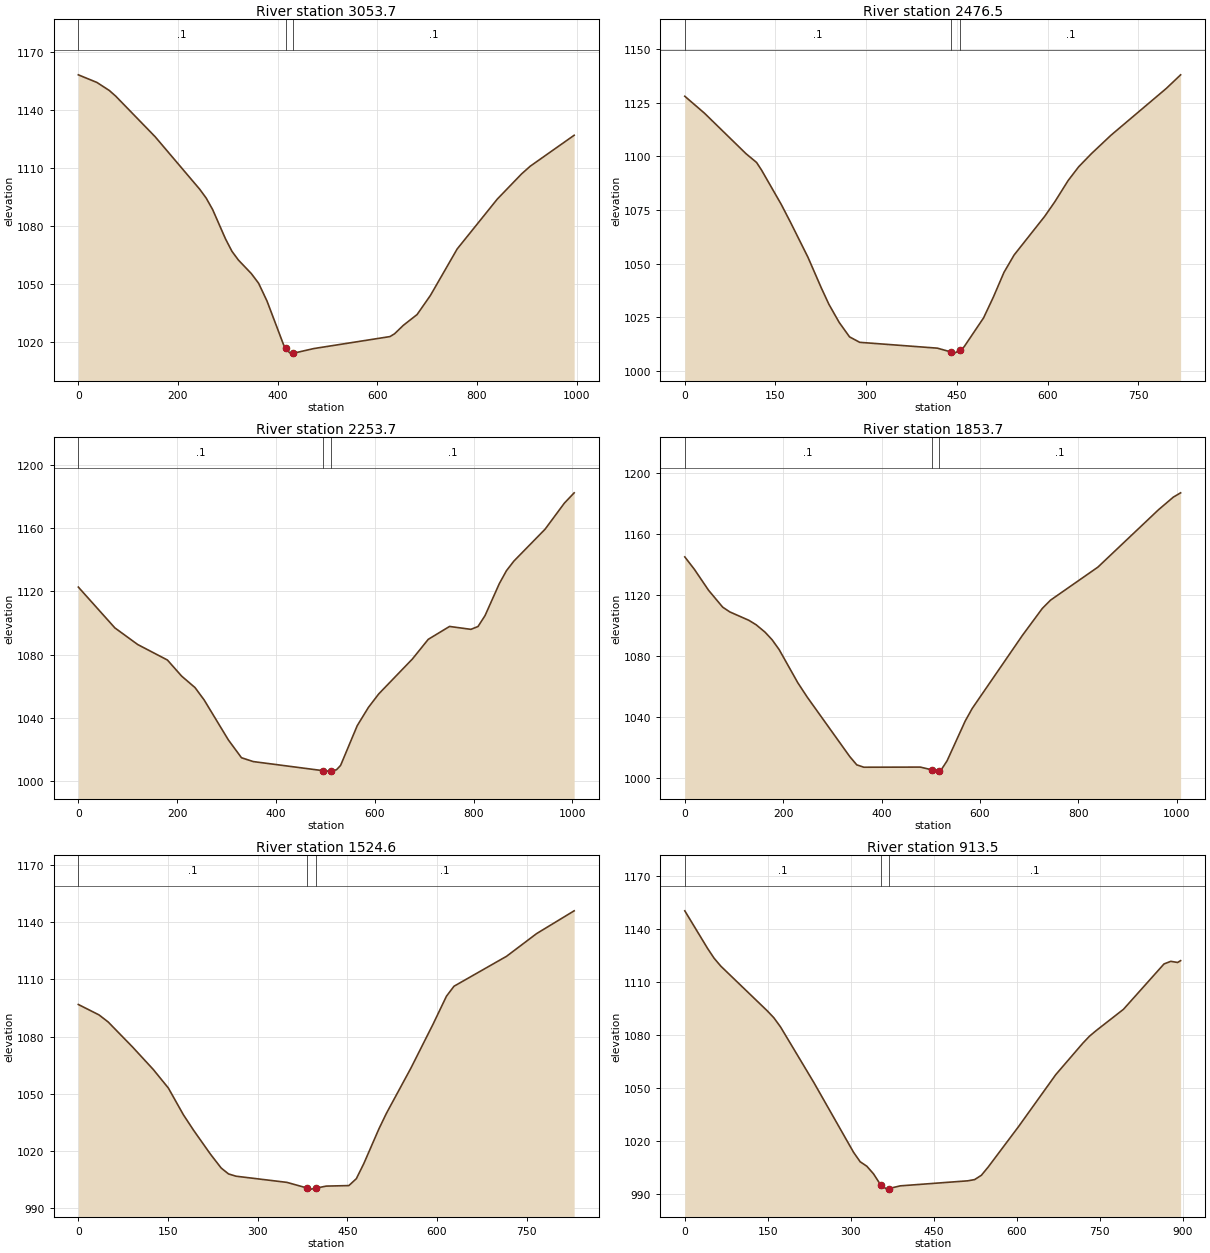
Type RM Length L Ch R = 1 ,3053.7,575.168,577.152,579.883
XS GIS Cut Line= 3
     1712437.517      346357.043     1712607.109      345968.167
     1712873.160      345462.835
#Sta/Elev= 30
       0 1158.35    37.4 1154.39    62.3 1150.21    75.3 1147.23   154.0 1126.31
   243.7 1099.02   256.6 1094.47   269.6 1088.50   295.5 1073.26   308.4 1066.84
   321.4 1062.31   347.3 1055.30   361.9 1050.29   378.8 1041.04   412.0 1018.41
   416.7 1016.68   423.9 1014.27   431.7 1014.09   432.7 1014.07   472.7 1016.44
   625.6 1022.65   634.8 1024.10   652.4 1028.48   680.0 1034.07   706.8 1044.00
   760.5 1068.08   841.0 1093.92   889.8 1106.99   907.3 1111.01   995.3 1127.02
#Mann= 3 , 0 , 0
       0     0.1       0   416.7   0.045       0   431.7     0.1       0
Bank Sta=   416.7,   431.7
Exp/Cntr=0.3,0.1

Type RM Length L Ch R = 1 ,2476.5,224.859,222.848,219.987
XS GIS Cut Line= 3
     1712789.348      346410.058     1713039.968      346034.128
     1713290.588      345764.230
#Sta/Elev= 30
       0 1127.92    32.5 1120.05   101.3 1101.18   118.8 1097.09   127.0 1093.54
   159.5 1077.62   175.2 1069.08   203.7 1053.02   225.8 1038.74   238.3 1031.15
   255.4 1022.68   272.5 1015.96   289.3 1013.43   417.8 1010.71     441 1008.88
   446.3 1008.40     456 1010.01   461.8 1011.28   494.2 1024.81   510.4 1034.49
   527.9 1045.96   544.7 1054.06   595.1 1071.98   611.9 1078.76   634.0 1088.68
   651.5 1095.11   672.4 1101.17   704.8 1109.76   796.7 1131.63   820.1 1137.89
#Mann= 3 , 0 , 0
       0     0.1       0     441   0.045       0     456     0.1       0
Bank Sta=     441,     456
Exp/Cntr=0.3,0.1

Type RM Length L Ch R = 1 ,2253.7,397.743,400,395.036
XS GIS Cut Line= 3
     1712982.607      346602.247     1713223.747      346160.186
     1713505.820      345747.394
#Sta/Elev= 30
       0 1122.79    73.9 1097.02   120.2 1086.49   180.3 1076.71   209.1 1066.54
   236.2 1059.28   254.7 1051.45   303.8 1026.16   330.2 1014.98   353.9 1012.55
   496.1 1006.76   506.9 1006.51   511.1 1006.74   522.3 1007.33   530.8 1010.11
   564.4 1035.20   587.0 1046.72   608.0 1055.30   676.1 1077.35   708.2 1089.77
   751.3 1097.92   794.5 1096.09   808.9 1097.87   823.2 1104.80   852.0 1124.95
   866.4 1133.10   881.6 1139.24   944.7 1159.37   983.6 1175.79  1003.5 1182.34
#Mann= 3 , 0 , 0
       0     0.1       0   496.1   0.045       0   511.1     0.1       0
Bank Sta=   496.1,   511.1
Exp/Cntr=0.3,0.1

Type RM Length L Ch R = 1 ,1853.7,335.111,329.077,327.919
XS GIS Cut Line= 3
     1713284.325      346779.209     1713570.159      346357.862
     1713754.771      345894.296
#Sta/Elev= 30
       0 1145.03    19.7 1136.78    48.3 1123.15    77.0 1112.07    91.4 1108.95
   130.2 1103.43   145.1 1100.49   163.1 1095.66   177.5 1090.66   191.8 1084.23
   229.7 1062.48   249.2 1052.89   335.3 1014.04   349.6 1008.58   364.0 1007.01
   478.7 1007.10   501.7 1005.35   515.3 1004.45   516.7 1004.57   520.4 1004.88
   533.2 1011.17   570.1 1037.31   584.3 1045.55   686.5 1093.56   726.9 1111.22
   743.7 1116.67   839.9 1138.32   963.1 1175.97   993.2 1184.24  1008.1 1187.08
#Mann= 3 , 0 , 0
       0     0.1       0   501.7   0.045       0   516.7     0.1       0
Bank Sta=   501.7,   516.7
Exp/Cntr=0.3,0.1

Type RM Length L Ch R = 1 ,1524.6,615.179,611.067,608.747
XS GIS Cut Line= 3
     1713724.899      346869.390     1713852.997      346505.211
     1713998.526      346085.676
#Sta/Elev= 30
       0 1096.81    34.6 1091.34    49.9 1087.63    90.5 1074.56   125.4 1062.68
   150.6 1052.95   175.8 1038.89   192.9 1030.74   220.8 1018.33   238.7 1011.06
   241.6 1010.28   251.3 1007.85   263.9 1006.65   349.0 1003.41   382.8 1000.44
   389.7  999.87   397.8 1000.41   414.8 1001.46   452.6 1001.73   465.1 1005.35
   477.7 1013.35   502.8 1031.45   515.4 1039.66   556.4 1063.41   593.7 1086.64
   615.9 1101.18   628.5 1106.39   716.4 1122.11   766.7 1134.03   829.5 1145.98
#Mann= 3 , 0 , 0
       0     0.1       0   382.8   0.045       0   397.8     0.1       0
Bank Sta=   382.8,   397.8
Exp/Cntr=0.3,0.1

Type RM Length L Ch R = 1 ,913.5,258.317,259.856,262.852
XS GIS Cut Line= 3
     1714355.723      347017.330     1714408.739      346651.039
     1714534.049      346140.160
#Sta/Elev= 30
       0 1150.38    41.1 1129.13    53.1 1123.48    65.1 1119.05   149.1 1093.71
   161.1 1089.75   173.1 1084.57   233.0 1053.26   305.0 1013.61   317.0 1008.24
   329.0 1005.72   341.0 1001.44   354.2  995.03   365.0  992.75   369.2  993.10
   389.4  994.60   511.6  997.46   523.8  998.15   536.0 1000.59   548.3 1005.26
   603.1 1028.13   670.5 1057.62   719.4 1075.42   731.6 1079.43   743.9 1082.65
   792.8 1094.60   866.1 1120.30   878.3 1121.77   890.6 1121.13   896.1 1122.16
#Mann= 3 , 0 , 0
       0     0.1       0   354.2   0.045       0   369.2     0.1       0
Bank Sta=   354.2,   369.2
Exp/Cntr=0.3,0.1

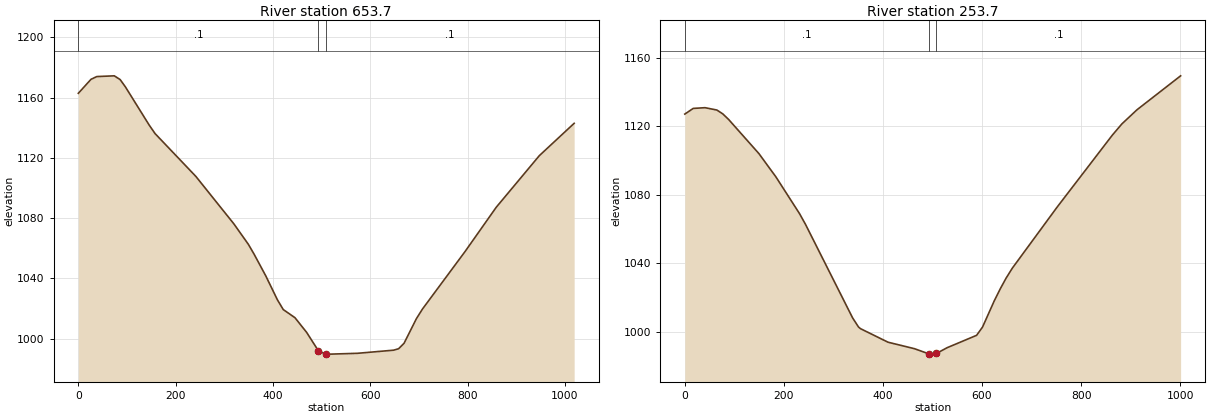
Type RM Length L Ch R = 1 ,653.7,400.901,400,393.831
XS GIS Cut Line= 3
     1714553.492      347168.658     1714618.172      346672.004
     1714794.709      346185.116
#Sta/Elev= 30
       0 1162.81    26.0 1172.09    38.0 1173.92    73.9 1174.41    85.9 1171.93
    96.8 1167.03   145.7 1141.66   157.7 1136.06   241.5 1107.64   319.5 1076.18
   349.3 1062.60   361.2 1055.99   385.2 1041.58   409.1 1025.70   421.1 1019.24
   445.1 1013.85   469.0 1004.15   493.3  991.87   508.3  989.72   517.8  989.66
   573.7  990.21   647.8  992.28   658.1  993.24   669.3  996.87   694.6 1013.17
   707.2 1019.63   794.6 1057.75   858.8 1087.20   947.2 1121.40  1018.8 1142.89
#Mann= 3 , 0 , 0
       0     0.1       0   493.3   0.045       0   508.3     0.1       0
Bank Sta=   493.3,   508.3
Exp/Cntr=0.3,0.1

Type RM Length L Ch R = 1 ,253.7,248.988,253.666,258.343
XS GIS Cut Line= 3
     1714968.665      347207.281     1715013.150      346708.761
     1715057.634      346210.242
#Sta/Elev= 30
       0 1127.20    17.0 1130.52    40.8 1130.94    64.7 1129.58    76.6 1127.35
    88.5 1124.06   149.6 1104.14   183.9 1090.55   231.5 1069.13   243.5 1062.91
   338.8 1008.18   350.7 1002.87   354.8 1001.88   410.3  993.98   463.7  990.19
     493  987.15   497.0  987.02     508  987.40   529.5  990.76   589.1  998.00
   601.1 1002.83   624.9 1018.22   636.8 1025.11   648.7 1031.42   661.2 1037.21
   751.6 1072.85   863.3 1114.97   882.5 1121.49   912.9 1129.72  1001.0 1149.55
#Mann= 3 , 0 , 0
       0     0.1       0     493   0.045       0     508     0.1       0
Bank Sta=     493,     508
Exp/Cntr=0.3,0.1